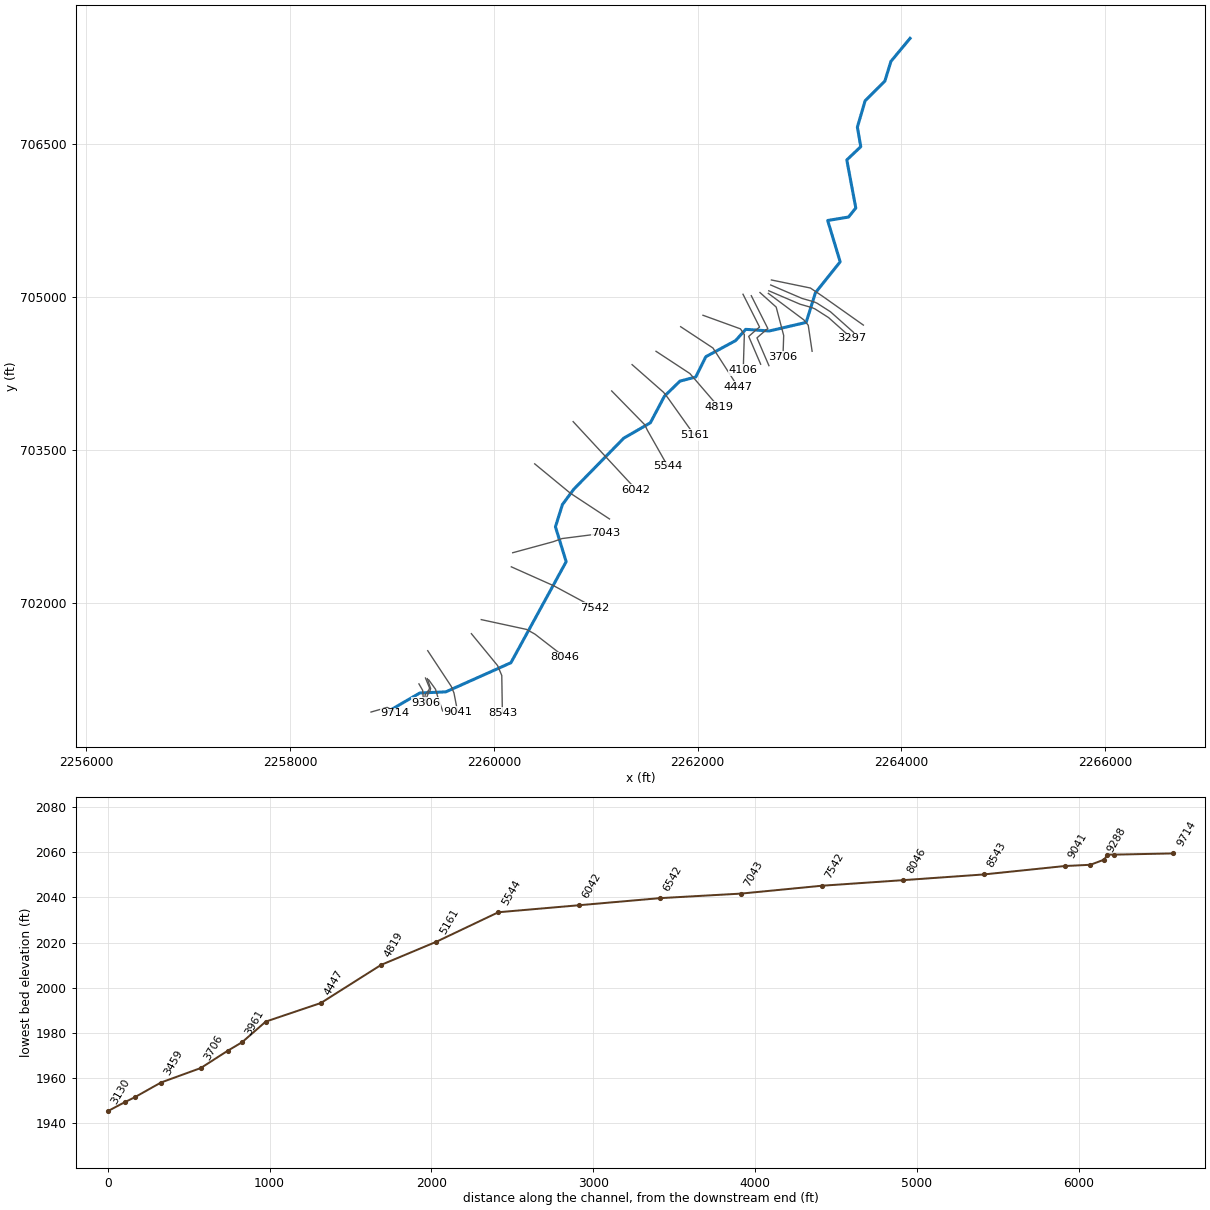
--- GRASSYRN.prj (project) ---

Proj Title=GRASSYRN
Current Plan=p01
Default Exp/Contr=0,0
English Units
Geom File=g01
Flow File=f01
Plan File=p01
BEGIN DESCRIPTION:
----------MODEL BY WOOD PLC 2022----------
AFH study
Randolph County, WV
HEC-RAS Version: RAS 6.2
Vertical Datum: NAVD88
Projection: NAD 1983 StatePlane West Virginia S FIPS 4702 (US Feet)
Terrain: 1-meter LIDAR (FEMA Region III 3DEP collected 2016-2018)
Land Use: 2019 NLCD
Hydrologic Method:
WV SIR2010-5033 regression equations
Additional Model Notes:
None
END DESCRIPTION:
DSS Export Rating Curves= 0
DSS Export Rating Curve Sorted= 0
DSS Export Volume Flow Curves= 0
DXF OffsetX= 0
DXF OffsetY= 0
DXF ScaleX= 0
DXF ScaleY= 0

--- GRASSYRN.p01 (plan) ---

Plan Title=Floodplain
Program Version=6.20
Short Identifier=Floodplain
Geom File=g01
Flow File=f01
Subcritical Flow
K Sum by GR= 0
Std Step Tol= 0.01
Critical Tol= 0.01
Num of Std Step Trials= 20
Max Error Tol= 0.3
Flow Tol Ratio= 0.001
Split Flow NTrial= 30
Split Flow Tol= 0.02
Split Flow Ratio= 0.02
Log Output Level= 0
Friction Slope Method= 1
Unsteady Friction Slope Method= 2
Unsteady Bridges Friction Slope Method= 1
Parabolic Critical Depth
Global Vel Dist= 0 , 0 , 0
Global Log Level= 0
CheckData=True
Encroach Param=-1 ,0,0, 0
Mapping Interval=1HOUR
Computation Time Step Use Courant=        0
Computation Time Step Use Time Series=    0
Computation Time Step Count To Double=0
Computation Time Step Max Doubling=0
Computation Time Step Max Halving=0
Computation Time Step Residence Courant=0
Run HTab= 0
Run UNet= 0
Run Sediment= 0
Run PostProcess= 0
Run WQNet= 0
Run RASMapper=-1
UNET Theta= 0
UNET Theta Warmup= 0
UNET ZTol= 0
UNET ZSATol= 0
UNET MxIter= 0
UNET Max Iter WO Improvement= 0
UNET MaxInSteps= 0
UNET DtIC= 0
UNET DtMin= 0
UNET MaxCRTS= 0
UNET WFStab= 0
UNET SFStab= 0
UNET WFX= 1
UNET SFX= 1
UNET Gravity=32.174
UNET 1D Methodology=Finite Difference
UNET DSS MLevel= 1
UNET Pardiso=0
UNET DZMax Abort= 0
UNET Use Existing IB Tables= 0
UNET Froude Reduction=False
UNET Froude Limit= 0
UNET Froude Power= 0
UNET D1 Cores= 0
UNET WindReference=Eulerian
UNET WindDragFormulation=Hsu (1988)
UNET D2 Coriolis=0
UNET D2 Cores= 0
UNET D2 Theta= 1
UNET D2 Theta Warmup= 1
UNET D2 Z Tol= 0.01
UNET D2 Volume Tol= 0.01
UNET D2 Max Iterations= 20
UNET D2 Equation= 0
UNET D2 RampUpFraction=0.1
UNET D2 TimeSlices= 1
UNET D2 Turbulence Formulation=Non-Conservative (original)
UNET D2 Eddy Viscosity=0.3
UNET D2 Transverse Eddy Viscosity=0.1
UNET D2 Smagorinsky Mixing=0
UNET D2 BCVolumeCheck=0
UNET D2 Cores=0
UNET D2 SolverType=PARDISO (Direct)
UNET D2 Minimum Iterations= 2147483647
UNET D2 Maximum Iterations= 2147483647
UNET D2 Restart Number= 10
UNET D2 Relaxation Coeff=1.3
UNET D2 SOR Precondition Iterations= 10
UNET D2 ILUT Maximum Fill= 8
UNET D2 ILUT Tolerance=1E-08
UNET D1D2 MaxIter= 0
UNET D1D2 ZTol=0.01
UNET D1D2 QTol=0.1
UNET D1D2 MinQTol=1
Write IC File= 0
Write IC File at Fixed DateTime=0
Write IC File at Sim End=0
Echo Input=False
Echo Parameters=False
Echo Output=False
Write Detailed= 0
HDF Write Warmup=0
HDF Write Time Slices=0
HDF Flush=0
HDF Compression= 1
HDF Chunk Size= 1
HDF Spatial Parts= 1
HDF Use Max Rows=0
HDF Fixed Rows= 1
Calibration Method= 0
Calibration Iterations= 20
Calibration Max Change=0.05
Calibration Tolerance=0.2
Calibration Maximum=1.5
Calibration Minimum=0.5
Calibration Optimization Method= 1
WQ AD Non Conservative
WQ ULTIMATE=-1
WQ Max Comp Step=1HOUR
WQ Output Interval=15MIN
WQ Output Selected Increments= 0
WQ Output face flow=0
WQ Output face velocity=0
WQ Output face area=0
WQ Output face dispersion=0
WQ Output cell volume=0
WQ Output cell surface area=0
WQ Output cell continuity=0
WQ Output cumulative cell continuity=0
WQ Output face conc=0
WQ Output face dconc_dx=0
WQ Output face courant=0
WQ Output face peclet=0
WQ Output face adv mass=0
WQ Output face disp mass=0
WQ Output cell mass=0
WQ Output cell source sink temp=0
WQ Output nsm pathways=0
WQ Output nsm derived pathways=0
WQ Create Restart=0
WQ Fixed Restart=0
WQ System Summary=0
WQ Write To DSS=0
Sorting and Armoring Iterations= 10
XS Update Threshold= 0.02
Bed Roughness Predictor= 0
Hydraulics Update Threshold= 0.02
Energy Slope Method= 1
Volume Change Method= 1
Sediment Retention Method= 0
Sediment TS Multiplier= 1
Warm Up Method= 0
XS Weighting Method= 0
Number of US Weighted Cross Sections= 1
Number of DS Weighted Cross Sections= 1
Upstream XS Weight=0
Main XS Weight=1
Downstream XS Weight=0
Number of DS XS's Weighted with US Boundary= 1
Upstream Boundary Weight= 1
Weight of XSs Associated with US Boundary= 0
Number of US XS's Weighted with DS Boundary= 1
Downstream Boundary Weight= 0.5
Weight of XSs Associated with DS Boundary= 0.5
Percentile Method= 0
Sediment Output Level= 3
Mass or Volume Output= 0
Output Increment Type= 1
Profile and TS Output Increment= 1
Transport Output Increment 1
XS Output Flag= 0
XS Output Increment= 10
Read HDF5 Sediment Hotstart= 0
Sediment Hotstart Type= 0
Write Gradation File= 0
Read Gradation Hotstart= 0
Write HDF5 File= 1
Write Binary Output= 1
Write DSS Sediment File= 0
DSS Sediment Output Type= 1
SV Curve= 0
Specific Gage Flag= 0
Subcell Erosion Methods= 0
Subcell Deposition Methods= 0
Advection Scheme= 1
Matrix Solver= 0
Implicit Weighting Factor= 1
Maximum Outer Loop Convergence Iterations= 5
Convergence Maximum Absolute= 0.001
Convergence RMSE= 0.0001
Grain Fractions Max Abs Error= 0.001
Max Subgrid Regions= 1
Max Subgrid Length Scale= 3.402823E+38
Initial Layer Thickness= 3.402823E+38
Min Layer Thickness= 3.402823E+38
Max Layer Thickness= 3.402823E+38
Number of Layers= 5

--- GRASSYRN.f01 (steady flow) ---

Flow Title=Flow
Program Version=6.20
Number of Profiles= 1
Profile Names=P100yr
River Rch & RM=GRASSYRN,Main,9714
     392
River Rch & RM=GRASSYRN,Main,7043
     436
River Rch & RM=GRASSYRN,Main,6542
     493
River Rch & RM=GRASSYRN,Main,2574
     705
Boundary for River Rch & Prof#=GRASSYRN,Main            , 1
Up Type= 0
Dn Type= 3
Dn Slope=0.02487
DSS Import GetInterval= 0
DSS Import GetPeak= 0
DSS Import FillOption= 0

--- GRASSYRN.g01 (geometry) ---

Geom Title=Geometry
Program Version=6.20

River Reach=GRASSYRN        ,Main
Reach XY= 30
2258983.06706534700945.1057022932259273.18097149701113.475573035
      2259527.93      701124.449     2260167.003      701410.298
     2260709.537      702402.485     2260603.982      702744.499
     2260672.732      702963.249     2260783.843      703113.249
     2261275.343      703615.2622261535.84272738703765.416272623
     2261673.708      704026.143     2261826.135      704174.666
     2261981.412      704215.332     2262080.344      704414.515
     2262372.384      704572.277     2262472.037       704683.04
     2262703.287      704667.068     2263065.013      704751.033
2263156.59862467705042.716281885     2263399.257      705345.721
     2263276.722       705751.53     2263481.242      705785.437
2263552.54855064705874.626304372     2263464.232      706345.927
2263601.27679628706476.0152852122263568.08814744706668.194836273
     2263643.957      706926.4252263837.88660728 707119.82501767
2263897.51188232707313.669531081     2264085.177      707539.712

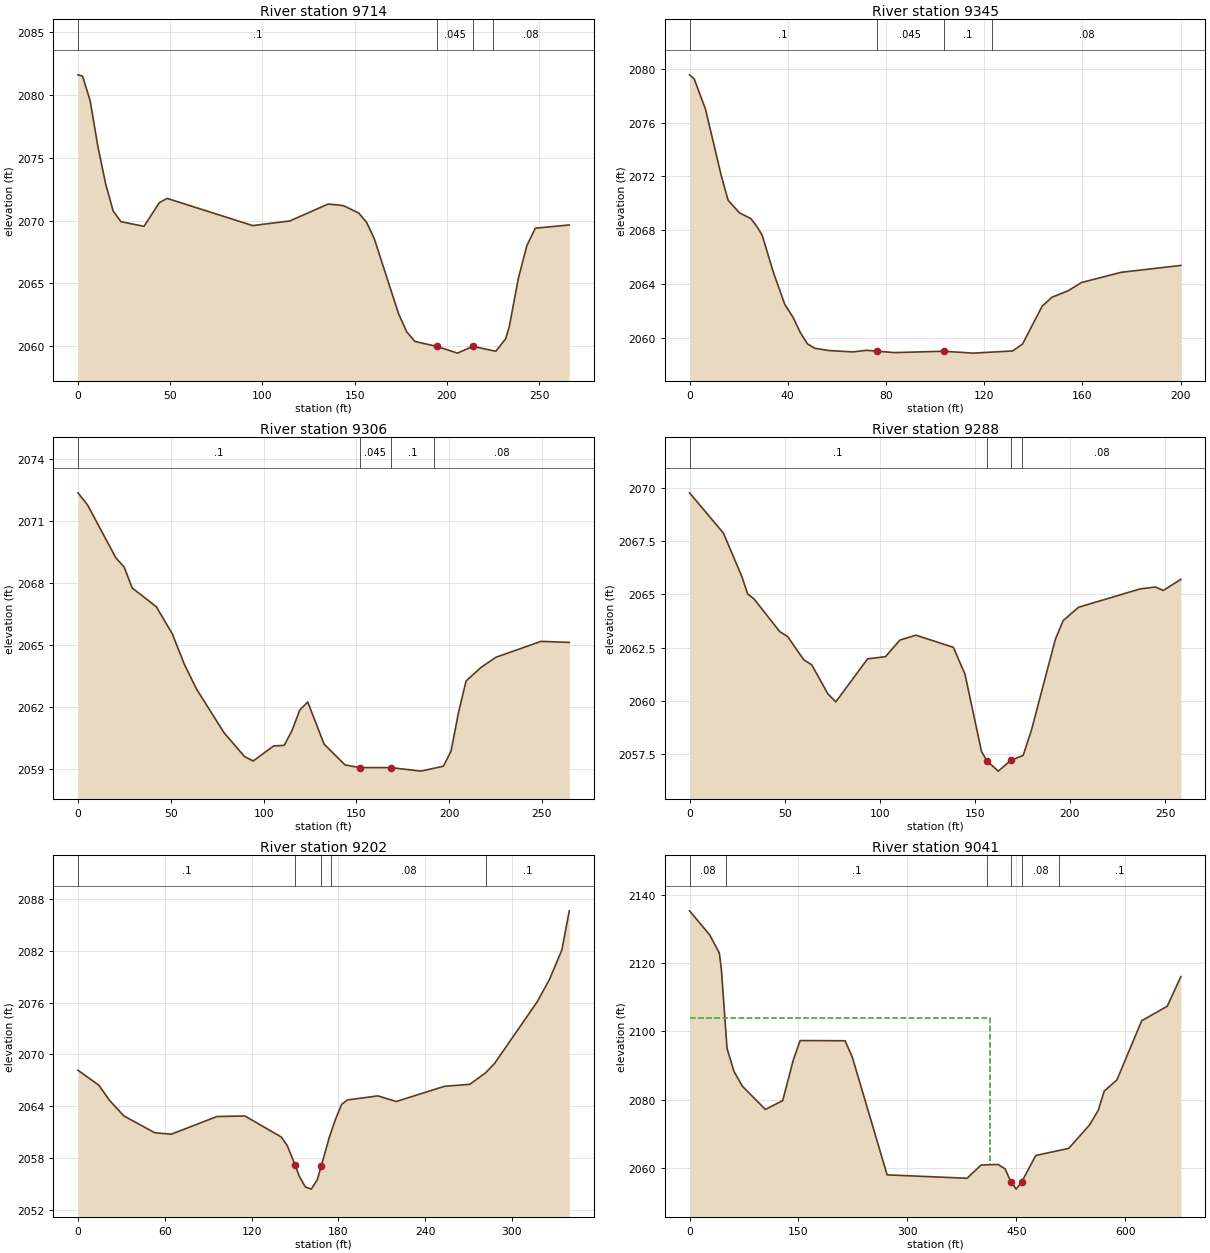
Type RM Length L Ch R = 1 ,9714    ,380.4,369.5,357.7
XS GIS Cut Line= 4
2258793.80960753 700926.280125112258952.29043071700972.045419322
2259014.50715338700940.8719660552259030.28499098 700913.25292784
#Sta/Elev= 30
       0 2081.62     2.5 2081.51     6.6 2079.55    10.8 2075.91      15 2072.93
    19.1 2070.76    23.3 2069.91    35.8 2069.54    44.1 2071.42    48.3 2071.77
    94.7  2069.6   114.9 2069.97   135.7 2071.32     144 2071.19   152.3 2070.59
   156.5 2069.86   160.7 2068.54   173.8 2062.59   178.2 2061.14   182.7 2060.36
  194.562059.969   205.8 2059.43     214 2059.97   226.6 2059.58   231.9 2060.57
   233.9 2061.56   238.8 2065.39   243.4    2068     248 2069.39   266.4 2069.65
#Mann= 4, -1 ,  0
       0     0.1       0  194.56   0.045       0     214     0.1       0
  224.96    0.08       0
Bank Sta=194.56,214
XS Rating Curve= 0 ,0
Exp/Cntr=0.3,0.1

Type RM Length L Ch R = 1 ,9345    ,45.1,39.1,31.6
XS GIS Cut Line= 3
2259264.19493031701202.803167987  2259300.763421701139.346081198
2259310.08480098701012.790422235
#Sta/Elev= 30
       0 2079.54     1.9 2079.23     6.5 2076.98    12.9 2072.06    15.7 2070.23
    20.3  2069.3      25 2068.86    27.5 2068.26    29.6 2067.62    34.2 2064.84
    38.8 2062.49    42.2 2061.52    45.1 2060.41      48 2059.57      51 2059.24
    56.8 2059.07    66.5 2058.97    72.1 2059.09   76.17 2059.03    83.4 2058.92
   103.5 2059.02   115.5 2058.88   131.6 2059.04   135.6 2059.55   143.6 2062.36
   147.6 2063.03   154.2 2063.51   159.6 2064.12   175.8 2064.88   200.1 2065.39
#Mann= 4, -1 ,  0
       0     0.1       0   76.17   0.045       0   103.5     0.1       0
  123.24    0.08       0
Bank Sta=76.17,103.5
XS Rating Curve= 0 ,0
Exp/Cntr(USF)=0,0
Exp/Cntr=0.3,0.1

Type RM Length L Ch R = 1 ,9306    ,18.3,18.2,19.7
XS GIS Cut Line= 6
2259328.62057272701260.2340829242259368.31664594701162.638056484
2259362.88633804701145.047026656 2259326.8469923701100.041478657
2259323.12125757701077.7763572052259331.74744651701018.145213733
#Sta/Elev= 30
       0 2072.37     5.1 2071.79    20.4 2069.22    24.9 2068.77    29.2 2067.76
    42.2 2066.85    50.8 2065.54    57.3 2064.06    63.8 2062.87    78.7 2060.74
    89.7 2059.59    94.4 2059.37   105.4  2060.1   111.1 2060.13   115.3 2060.84
   119.5 2061.84   123.8 2062.23   132.6 2060.19   143.9 2059.18  151.822059.051
   168.6 2059.05   184.8 2058.88   196.9 2059.12     201 2059.85     205 2061.71
   209.1 2063.25   217.2 2063.91   225.2  2064.4   249.5 2065.17   264.7 2065.12
#Mann= 4, -1 ,  0
       0     0.1       0  151.82   0.045       0   168.6     0.1       0
  191.85    0.08       0
Bank Sta=151.82,168.6
XS Rating Curve= 0 ,0
Exp/Cntr(USF)=0,0
Exp/Cntr=0.3,0.1

Type RM Length L Ch R = 1 ,9288    ,82.5,86,92.4
XS GIS Cut Line= 6
2259346.25692671701254.0687068952259379.17705049701156.472680455
2259371.59075868 701131.489705792259359.81107887701121.260389048
2259340.75761155701071.6109811762259349.38380049701011.979837704
#Sta/Elev= 30
       0 2069.77    17.8 2067.88    27.5 2065.84    30.5 2065.03    33.8  2064.8
    47.4 2063.26    51.6 2063.02      60 2061.94    64.3 2061.69    72.7 2060.34
    76.9 2059.96    93.6 2061.98     103 2062.08   110.6 2062.86     119 2063.09
   138.7 2062.52   144.8 2061.26   153.5 2057.63  156.322057.193   162.3 2056.71
   168.8 2057.21   175.4 2057.45   179.8 2058.65   192.3 2062.89   196.4 2063.77
   204.5  2064.4   236.9 2065.26   244.9 2065.35   249.1 2065.19   258.3 2065.71
#Mann= 4, -1 ,  0
       0     0.1       0  156.32   0.045       0   168.8     0.1       0
  174.71    0.08       0
Bank Sta=156.32,168.8
XS Rating Curve= 0 ,0
Exp/Cntr(USF)=0,0
Exp/Cntr=0.3,0.1

Type RM Length L Ch R = 1 ,9202    ,159.3,160.2,160.9
XS GIS Cut Line= 4
2259359.75066231701242.8572337872259426.88017202701149.908681886
2259451.76033995701065.8794354712259497.29574164700936.314787367
#Sta/Elev= 30
       0 2068.17    14.4 2066.44    21.8 2064.68    31.7 2062.88    53.1 2060.93
    64.5 2060.76    96.1 2062.81   115.4 2062.87   140.4 2060.45   144.6 2059.47
  150.182057.149     153 2055.89   157.1 2054.66   161.3  2054.4   165.5 2055.52
  168.172057.083   173.8 2060.44     178 2062.48   182.2 2064.21   186.3 2064.73
   207.3  2065.2     220 2064.55   253.4 2066.31   270.9 2066.54   281.6 2067.85
   287.9 2068.94   317.5 2076.11     326 2078.71   334.5  2082.1   339.6 2086.63
#Mann= 5, -1 ,  0
       0     0.1       0  150.18   0.045       0  168.17     0.1       0
  174.66    0.08       0  282.29     0.1       0
Bank Sta=150.18,168.17
XS Rating Curve= 0 ,0
Exp/Cntr(USF)=0,0
Exp/Cntr=0.3,0.1

Type RM Length L Ch R = 1 ,9041    ,498.7,498.8,498.8
XS GIS Cut Line= 4
2259350.44893975701528.2764109232259580.78629389701179.316059385
 2259607.9396654701114.0696559322259643.72706815700929.631644233
#Sta/Elev= 30
       0 2135.28    27.7 2128.24      41 2122.93    43.9 2117.93    51.6 2095.02
    61.2 2088.25    72.8 2083.94   104.5 2077.15   128.3 2079.74   142.7 2091.51
   152.3 2097.32   214.2 2097.25   224.2 2092.44   272.1 2058.01   382.3 2057.01
   401.5 2060.89   424.8 2061.06   434.6 2059.77   442.42056.057   449.9 2053.83
   457.72056.032   476.8 2063.67   522.3 2065.76   551.2 2072.68     563 2076.93
   571.2 2082.53   588.7 2085.81   622.8 2103.13     658 2107.36   676.7 2116.05
#Mann= 6, -1 ,  0
       0    0.08       0      50     0.1       0     410    0.08       0
   442.4   0.045       0   457.7    0.08       0   508.8     0.1       0
#XS Ineff= 2 , 0
          413.29 2103.91
Permanent Ineff=
       F       F
Bank Sta=442.4,457.7
XS Rating Curve= 0 ,0
Exp/Cntr=0.3,0.1

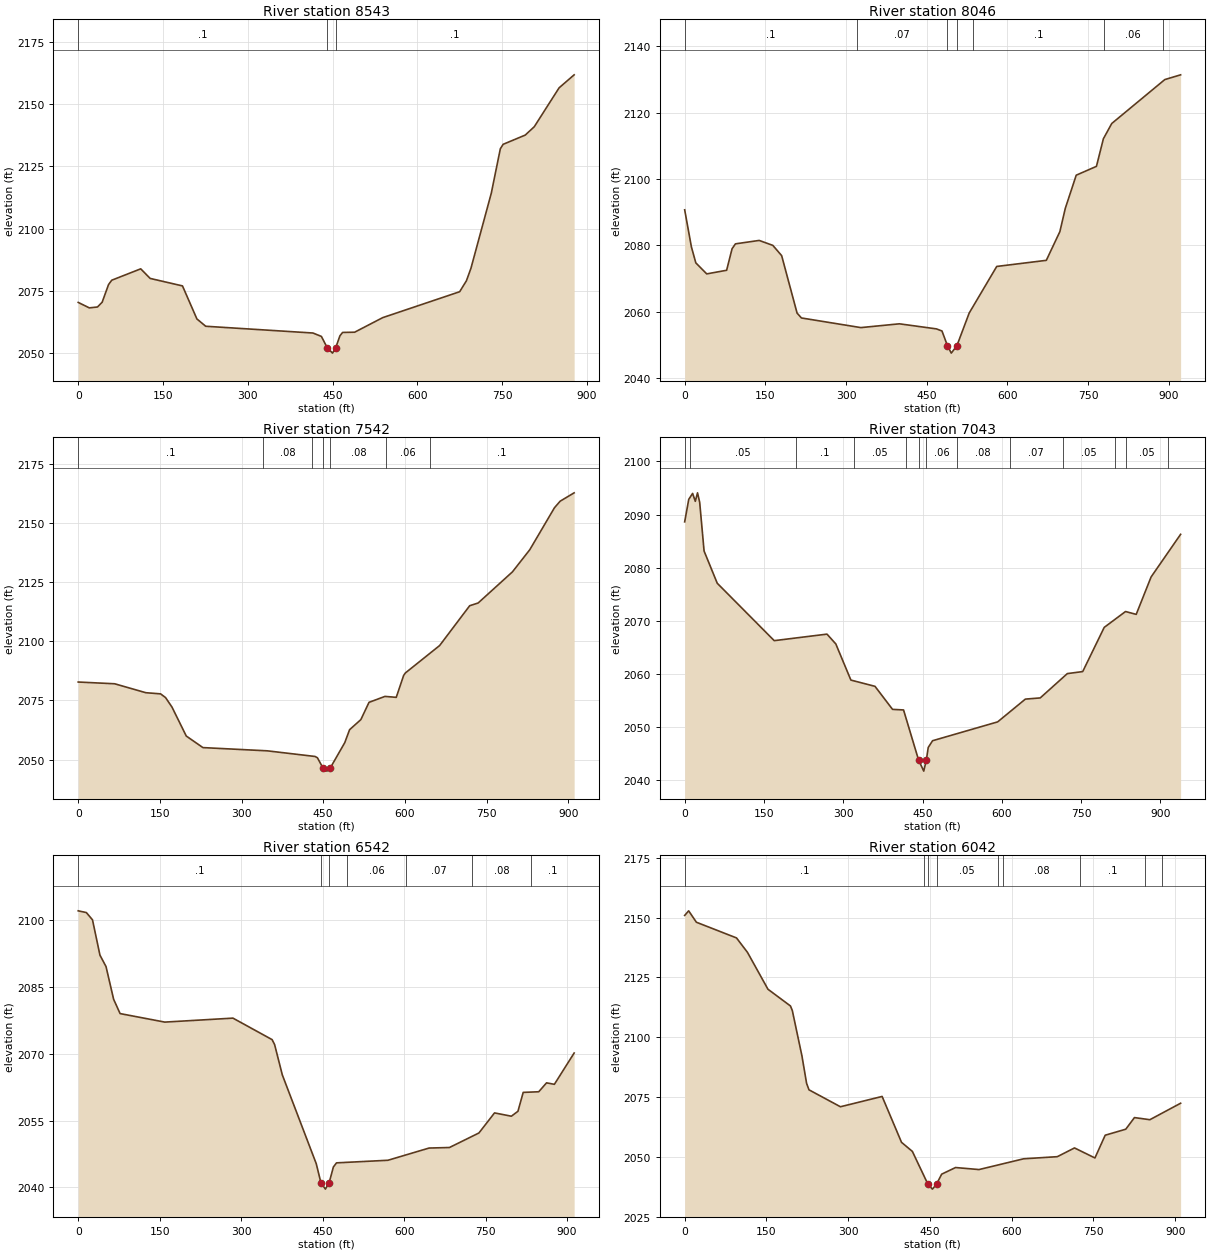
Type RM Length L Ch R = 1 ,8543    ,490.8,496.5,500.9
XS GIS Cut Line= 4
2259778.90927366 701695.555273662260036.41779849701381.987447802
2260077.34171472701284.9750836362260083.20267634700918.571427678
#Sta/Elev= 30
       0 2070.47    19.6 2068.28    34.1 2068.63    42.4 2070.56    53.7 2077.64
    59.4 2079.38   110.6 2083.94   127.3 2080.09   184.5 2077.09     210 2063.84
   225.6  2060.9   415.3 2058.19   430.3 2056.82  440.632052.269     450 2050.12
  455.572052.268   463.1 2057.08   467.8 2058.42   489.1 2058.51   538.8 2064.36
   674.9 2074.75   686.9 2079.16   694.9 2084.17   730.9 2114.29   746.9 2132.12
   751.9  2133.9   790.9  2137.6   806.9 2140.94   850.9 2156.57   877.5 2161.78
#Mann= 3, -1 ,  0
       0     0.1       0  440.63   0.045       0  455.57     0.1       0
Bank Sta=440.63,455.57
XS Rating Curve= 0 ,0
Exp/Cntr=0.3,0.1

Type RM Length L Ch R = 1 ,8046    ,503.8,504.5,504.7
XS GIS Cut Line= 4
2259875.94302268701833.6357920572260321.30046987701737.261941483
2260402.68144226701691.290630035 2260697.7489017701463.225132323
#Sta/Elev= 30
       0 2090.72    12.5 2079.57    20.7 2074.76      41 2071.44      78 2072.53
    88.1    2079    94.4 2080.48   138.5 2081.51   163.9 2080.02   180.3 2076.94
     209 2059.64   217.1 2058.18   327.6 2055.28   399.3 2056.42   468.2 2054.89
   478.4 2054.26  488.642049.812   495.7  2047.6   506.12049.811     529 2059.66
   580.2 2073.68   672.4 2075.52   697.6 2084.16   707.7 2091.17     728 2101.14
   765.6  2103.8   778.5  2112.1   794.1  2116.7   892.7 2129.91   922.1 2131.34
#Mann= 7, -1 ,  0
       0     0.1       0     320    0.07       0  488.64   0.045       0
   506.1    0.07       0  535.67     0.1       0  779.13    0.06       0
  889.13     0.1       0
Bank Sta=488.64,506.1
XS Rating Curve= 0 ,0
Exp/Cntr=0.3,0.1

Type RM Length L Ch R = 1 ,7542    ,493.3,499,504.8
XS GIS Cut Line= 3
     2260170.961      702351.806     2260587.515      702165.854
     2260987.947      701950.236
#Sta/Elev= 30
       0  2082.8      67 2082.06   124.2 2078.28   151.3 2077.79   160.4 2076.23
   172.2 2072.23   198.5 2059.96   229.1 2055.07   347.4  2053.7     435 2051.32
   439.4 2050.78  449.232046.626   456.9 2045.12  463.392046.627   489.6 2057.14
   498.5 2062.64   519.2 2066.91   534.2 2074.21   563.5 2076.72   584.2 2076.32
   597.8 2085.59     601 2086.64   663.9 2098.23   719.1 2115.06   734.7 2116.23
   797.7  2129.4   829.5 2138.75   874.9 2156.52   885.3 2159.27     911 2162.81
#Mann= 7, -1 ,  0
       0     0.1       0     340    0.08       0     430     0.1       0
  449.23   0.045       0  463.39    0.08       0  566.17    0.06       0
  646.17     0.1       0
Bank Sta=449.23,463.39
XS Rating Curve= 0 ,0
Exp/Cntr=0.3,0.1

Type RM Length L Ch R = 1 ,7043    ,508.5,501,493.9
XS GIS Cut Line= 4
     2260184.741      702490.199 2260579.6912038702597.531056776
2260669.62543325702629.431953213      2261099.54       702684.32
#Sta/Elev= 30
       0 2088.62     7.7 2092.86      15 2093.98    20.1 2092.49    24.3 2094.09
    28.4 2092.29    36.7 2083.12    61.6 2077.05   169.4 2066.23   269.2 2067.46
   285.9 2065.61   314.4  2058.8     360 2057.62   393.2 2053.28     414 2053.17
   442.42043.754   452.2 2041.64  457.162043.752   460.7  2046.1   468.9 2047.37
     592 2050.92   644.4 2055.21   672.6 2055.44   723.8 2060.02   752.9  2060.4
   793.6 2068.73   833.9 2071.72   854.1 2071.18   882.3 2078.24   938.1 2086.27
#Mann= 13, -1 ,  0
       0     0.1       0      10    0.05       0     210     0.1       0
     320    0.05       0  419.27    0.06       0   442.4   0.045       0
  457.16    0.06       0   514.7    0.08       0   614.7    0.07       0
   714.7    0.05       0   814.7     0.1       0   834.7    0.05       0
   914.7     0.1       0
Bank Sta=442.4,457.16
XS Rating Curve= 0 ,0
Exp/Cntr=0.3,0.1

Type RM Length L Ch R = 1 ,6542    ,501.1,500,498.2
XS GIS Cut Line= 3
     2260400.629      703362.605      2260751.34      703073.781
     2261134.634      702821.646
#Sta/Elev= 30
       0 2102.03      15 2101.64    26.3 2100.01      40  2092.1    51.2 2089.53
    65.2  2082.2    77.1 2078.99   159.5 2077.08   284.9 2077.97     357 2073.15
   361.6 2072.04   375.8 2065.24   438.3 2045.32  446.822041.082   455.1 2039.63
  462.042041.081   469.8 2044.59   475.6 2045.52   570.2  2046.1     646 2048.84
   683.5 2048.96   737.8 2052.22   766.5 2056.72   797.5 2055.98   809.6 2057.08
   819.3 2061.32   847.9 2061.46   862.3 2063.46   876.7 2063.13   913.1 2070.15
#Mann= 7, -1 ,  0
       0     0.1       0  446.82   0.045       0  462.04     0.1       0
  494.33    0.06       0  604.33    0.07       0  724.33    0.08       0
  834.33     0.1       0
Bank Sta=446.82,462.04
XS Rating Curve= 0 ,0
Exp/Cntr=0.3,0.1

Type RM Length L Ch R = 1 ,6042    ,500.1,497.9,495.9
XS GIS Cut Line= 3
     2260777.874      703777.249     2261087.205      703443.573
     2261396.535      703109.896
#Sta/Elev= 30
       0 2150.92     7.3 2152.85    21.5 2148.08    95.1 2141.52   115.2 2135.49
   152.8 2120.07   194.1 2113.07   197.5 2111.17   215.2 2092.16   223.7 2080.71
   228.1 2078.01   285.8 2070.93   362.3 2075.24   397.9 2056.05   417.8 2052.26
  446.332038.543   454.6 2036.49  462.112038.543   471.5 2042.74     497 2045.52
   540.1 2044.67   621.9 2049.17   683.8 2050.06   715.3 2053.71   752.8 2049.52
   771.6 2059.03   809.4 2061.55   825.3  2066.4   853.6 2065.52     910  2072.4
#Mann= 9, -1 ,  0
       0     0.1       0     440    0.05       0  446.33   0.045       0
  462.11    0.05       0     575    0.06       0     585    0.08       0
     725     0.1       0     845    0.06       0     875     0.1       0
Bank Sta=446.33,462.11
XS Rating Curve= 0 ,0
Exp/Cntr=0.3,0.1

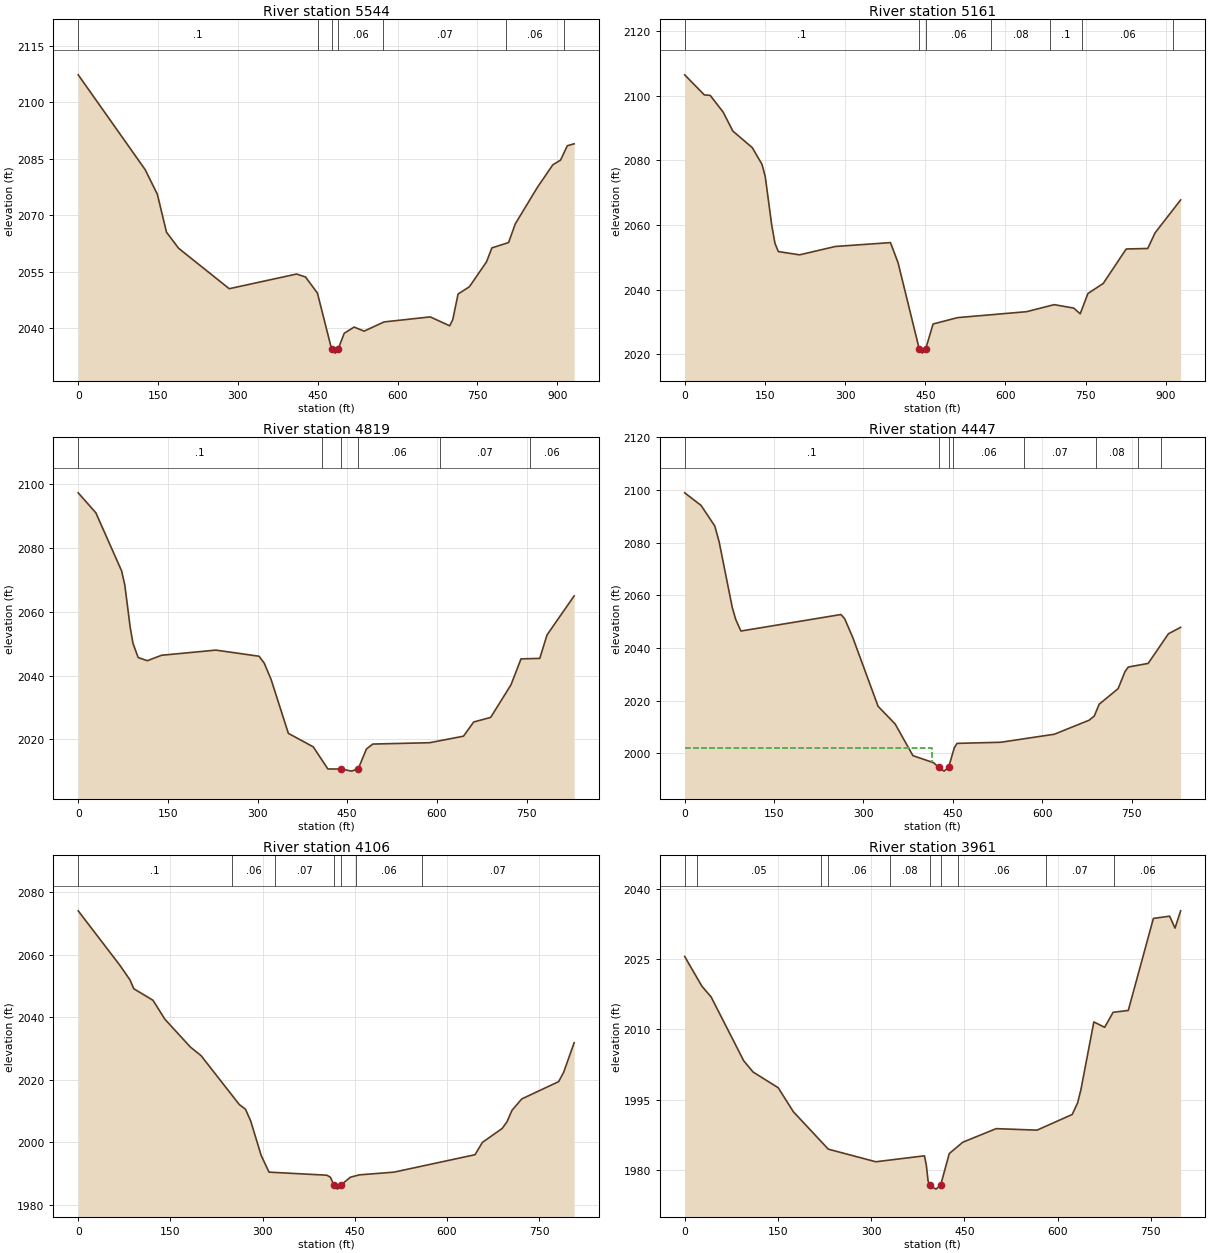
Type RM Length L Ch R = 1 ,5544    ,380.2,382.5,382.8
XS GIS Cut Line= 4
     2261156.175      704078.3712261480.91716577703746.478453792
2261506.29667277703693.2860539762261707.68456607703338.006996875
#Sta/Elev= 30
       0 2107.26   125.8 2082.09   148.7 2075.55   165.9 2065.47   188.7 2061.21
   283.7 2050.49   410.2 2054.38     427 2053.61   449.4 2049.33  475.922034.528
   482.8 2033.39  488.382034.525   499.8 2038.66   518.3 2040.31   537.2 2039.23
   574.6 2041.67   661.3 2043.01   697.9 2040.64   703.7  2042.3   713.6 2049.07
   734.9 2051.01   767.1 2057.63   777.1 2061.32   808.5 2062.74   821.1  2067.7
   862.2 2077.29   891.5 2083.36   906.2 2084.63   918.8 2088.43   931.7 2088.96
#Mann= 7, -1 ,  0
       0     0.1       0     450    0.06       0  475.92   0.045       0
  488.38    0.06       0  573.28    0.07       0  803.28    0.06       0
  913.28     0.1       0
Bank Sta=475.92,488.38
XS Rating Curve= 0 ,0
Exp/Cntr=0.3,0.1

Type RM Length L Ch R = 1 ,5161    ,338.5,342.1,342.2
XS GIS Cut Line= 4
2261356.51029016704336.7479934372261666.33801011 704064.18388345
2261709.39219346 704008.234082082261967.02829016703646.212993437
#Sta/Elev= 30
       0 2106.51    36.8 2100.29    47.8 2100.14      72 2094.96    90.1  2089.1
   126.5 2083.96   144.7 2078.77   150.7    2075   162.9  2059.9   168.9 2054.33
   175.2 2051.79   214.9 2050.78   281.9 2053.37   384.9 2054.57   399.1 2048.35
  438.61 2021.73   444.6 2020.35  450.91 2021.73   464.6 2029.37   510.4 2031.34
   639.5 2033.18   691.1 2035.36   727.6  2034.3   739.8 2032.53   754.2  2038.8
   782.9 2041.93   825.8 2052.59   866.1 2052.75   879.8 2057.58   927.6 2067.78
#Mann= 7, -1 ,  0
       0     0.1       0  438.61   0.045       0  450.91    0.06       0
  573.25    0.08       0  683.25     0.1       0  743.25    0.06       0
  913.25     0.1       0
Bank Sta=438.61,450.91
XS Rating Curve= 0 ,0
Exp/Cntr=0.3,0.1

Type RM Length L Ch R = 1 ,4819    ,366.1,371.6,368.5
XS GIS Cut Line= 4
2261591.52471874704467.4540742892261923.62452204704249.367182053
2261987.93778209704175.0891466862262205.83896297703921.706294238
#Sta/Elev= 30
       0 2097.26    29.5 2091.01    72.6 2072.81      78 2068.33    86.9 2055.24
    91.6 2050.14   100.3 2045.67   115.6 2044.67   139.6 2046.38   230.3 2047.99
   302.5 2046.07   311.2 2043.92   322.7  2038.8   351.6 2021.91   393.2 2017.69
   417.7 2010.76   440.4 2010.73   457.4 2010.08  468.492010.825   482.2 2017.01
   492.8 2018.56   587.9 2018.98   644.6 2021.03   661.6 2025.47     690 2026.91
     724 2037.11   740.8 2045.24   772.2  2045.4   784.3 2052.74   829.7 2064.97
#Mann= 6, -1 ,  0
       0     0.1       0  407.31    0.06       0   440.4   0.045       0
  468.49    0.06       0  605.56    0.07       0  755.56    0.06       0
Bank Sta=440.4,468.49
XS Rating Curve= 0 ,0
Exp/Cntr(USF)=0,0
Exp/Cntr=0.3,0.1

Type RM Length L Ch R = 1 ,4447    ,340.2,341.1,341
XS GIS Cut Line= 3
2261833.22825249 704708.979530922262150.49125818704499.735945781
2262395.26555219704119.276481389
#Sta/Elev= 30
       0 2098.96    27.5 2094.19    50.5 2086.37    57.8 2080.38    79.9 2055.39
    85.7 2050.84    94.4 2046.46   262.3 2052.73   268.5 2051.15   282.1 2044.02
   324.6 2017.88   353.3 2011.13   383.1 1999.13   417.9 1996.43  426.151994.705
   435.4 1993.24  442.961994.707   452.6 2002.14   457.1 2003.78   530.7 2004.21
   620.4 2007.25   678.9 2012.59   687.5 2014.17   695.7 2018.66   727.5 2024.57
   739.1 2031.08   744.6 2032.78   777.9 2034.16     812 2045.43   832.4 2047.86
#Mann= 8, -1 ,  0
       0     0.1       0  426.15   0.045       0  442.96     0.1       0
  450.05    0.06       0  570.05    0.07       0  690.05    0.08       0
  760.05    0.06       0  800.05     0.1       0
#XS Ineff= 2 , 0
          414.63  2002.1
Permanent Ineff=
       F       F
Bank Sta=426.15,442.96
XS Rating Curve= 0 ,0
Exp/Cntr=0.3,0.1

Type RM Length L Ch R = 1 ,4106    ,156.5,145.8,136.3
XS GIS Cut Line= 4
2262052.32582338704821.2829176952262420.22307034704687.810725689
 2262458.5049722704631.2707109262262447.62917785704283.934625261
#Sta/Elev= 30
       0 2074.01    67.9 2056.57    84.3  2051.9    90.5 2049.08   121.7  2045.4
     141 2039.35   182.8 2030.39   199.8 2027.72   262.2 2012.04   272.2 2010.56
   280.7  2006.8   297.7 1995.81   310.5 1990.43   404.7 1989.44   410.5 1988.78
  416.151986.229     422 1984.99  427.231986.226   442.8 1988.79   457.3 1989.55
   513.8 1990.42   645.8    1996   657.8 1999.95   689.8 2004.37   697.8 2006.52
   705.9 2010.19   721.9 2013.85   781.9 2019.38   789.9 2022.31   807.1 2031.82
#Mann= 7, -1 ,  0
       0     0.1       0     250    0.06       0     320    0.07       0
  416.15   0.045       0  427.23    0.07       0  451.36    0.06       0
  559.64    0.07       0
Bank Sta=416.15,427.23
XS Rating Curve= 0 ,0
Exp/Cntr(USF)=0,0
Exp/Cntr=0.3,0.1

Type RM Length L Ch R = 1 ,3961    ,91.9,89,93.3
XS GIS Cut Line= 5
2262445.37629411705027.4871755832262607.69774655704705.764373014
2262533.96478928704642.5646953532262501.31162248704613.598176424
2262618.56639144704340.921553585
#Sta/Elev= 30
       0 2025.53    27.6  2019.2    42.5  2016.9      95 2003.26   110.1 2000.86
   150.4 1997.52   174.9 1992.38   231.1  1984.4   307.5 1981.71   385.8 1982.98
   388.8 1980.97   391.6 1977.63  394.611976.662   404.3 1975.87  411.711976.665
   425.7 1983.46   447.3 1985.87   501.1 1988.78   566.9 1988.46   623.5  1991.8
   632.2 1994.29   637.6 1997.18   658.3 2011.56   675.7 2010.41   689.3 2013.61
   713.7 2014.01   754.1 2033.65   780.2 2034.13   788.9 2031.58   797.9 2035.27
#Mann= 10, -1 ,  0
       0     0.1       0      20    0.05       0     220    0.07       0
     230    0.06       0     330    0.08       0  394.61   0.045       0
  411.71    0.08       0  440.35    0.06       0  581.11    0.07       0
  691.11    0.06       0
Bank Sta=394.61,411.71
XS Rating Curve= 0 ,0
Exp/Cntr(USF)=0,0
Exp/Cntr=0.3,0.1

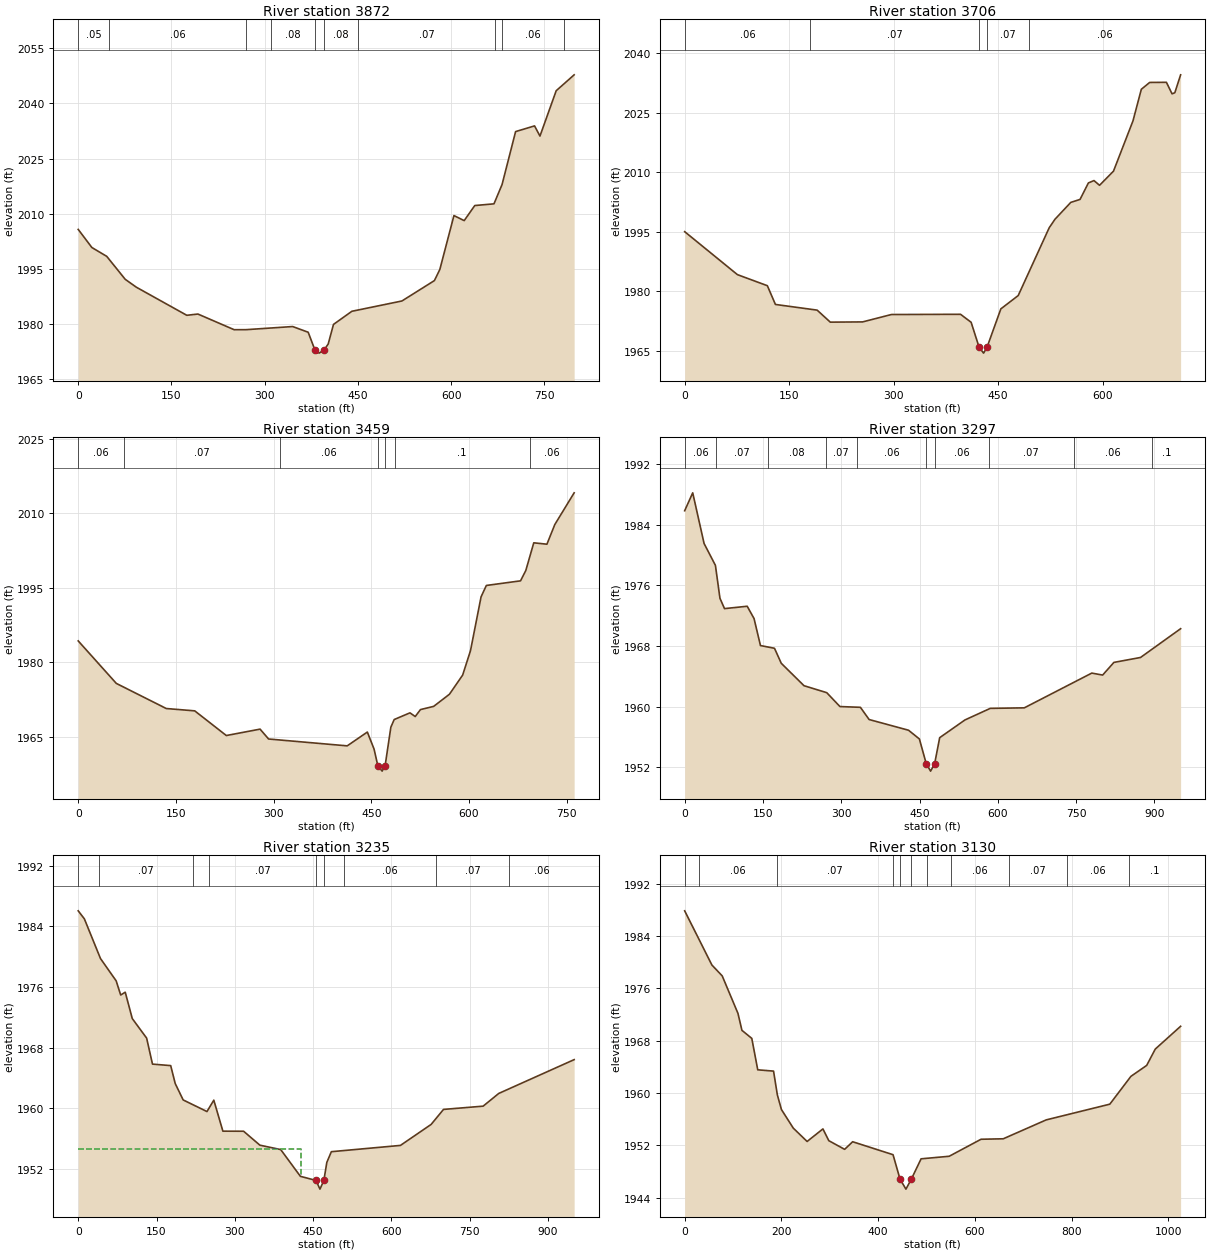
Type RM Length L Ch R = 1 ,3872    ,153.5,166,168.1
XS GIS Cut Line= 5
2262526.56452102705013.1656879322262688.88597346704691.442885363
2262615.15301619704628.2432077022262582.49984939704599.276688773
2262699.75461835704326.600065934
#Sta/Elev= 30
       0 2005.74      22 2000.81    45.9 1998.41    75.6 1992.17    93.5 1990.02
   174.7 1982.38   192.6 1982.72   250.9 1978.46     270 1978.47     345 1979.32
     370 1977.77  380.691973.015   387.6 1972.09   395.91973.016   402.2 1974.57
   410.7  1979.9   440.3 1983.47   520.8 1986.27   573.1 1991.82   581.8 1994.84
   604.5  2009.5     621 2008.13     638 2012.23   668.9 2012.69   681.9 2017.93
   703.7 2032.34   734.2 2033.89   742.9 2031.12     769 2043.45   797.9 2047.78
#Mann= 10, -1 ,  0
       0    0.05       0      50    0.06       0     270    0.07       0
     310    0.08       0  380.69   0.045       0   395.9    0.08       0
  450.35    0.07       0  671.11     0.1       0  681.11    0.06       0
  781.11     0.1       0
Bank Sta=380.69,395.9
XS Rating Curve= 0 ,0
Exp/Cntr(USF)=0,0
Exp/Cntr=0.3,0.1

Type RM Length L Ch R = 1 ,3706    ,242.3,246.5,247.1
XS GIS Cut Line= 4
2262611.84270649705044.1925947662262771.02867191704901.427323755
2262844.67711626704622.6775741342262837.60425239704412.832600789
#Sta/Elev= 30
       0 1995.08    75.7 1984.25   118.7 1981.46   130.3 1976.73   190.2  1975.3
   209.1 1972.27   255.5 1972.33   296.8 1974.19   396.1 1974.25   411.3 1972.24
  422.78 1965.93   429.2 1964.46  434.121965.928     454 1975.62   478.9 1978.97
   523.4 1996.06   531.7 1998.21   554.4 2002.46   567.7 2003.21   579.7 2007.37
   587.7 2007.96   595.7 2006.77   615.7 2010.33   643.7 2023.01   655.7 2030.98
   667.7  2032.7   691.7 2032.73   699.8 2029.83   703.8 2030.11   712.1 2034.62
#Mann= 5, -1 ,  0
       0    0.06       0     180    0.07       0  422.78   0.045       0
  434.12    0.07       0  493.83    0.06       0
Bank Sta=422.78,434.12
XS Rating Curve= 0 ,0
Exp/Cntr(USF)=0,0
Exp/Cntr=0.3,0.1

Type RM Length L Ch R = 1 ,3459    ,156.9,161.7,163.1
XS GIS Cut Line= 4
2262693.90485634705036.1701093342263043.02614124704775.613517917
2263085.74937247704722.982834831 2263123.6976649704467.781556714
#Sta/Elev= 30
       0 1984.26    58.5  1975.7   135.2 1970.64   178.9 1970.17   227.4  1965.2
   279.2 1966.49   292.3  1964.5     413 1963.12   443.9  1965.9   454.2 1962.48
  459.951959.148   466.6 1958.03  471.211959.145     480 1966.88   485.1 1968.42
   509.3 1969.77   517.4 1969.03   525.5 1970.43   545.7 1971.07   569.9 1973.51
   590.2 1977.37   602.3 1982.31   618.5 1993.14   626.6 1995.43   679.1 1996.36
   687.2 1998.45   699.4 2004.02   719.6 2003.74   731.7  2007.7   761.4 2014.09
#Mann= 7, -1 ,  0
       0    0.06       0      70    0.07       0     310    0.06       0
  459.95   0.045       0  471.21    0.06       0  485.63     0.1       0
  693.42    0.06       0
Bank Sta=459.95,471.21
XS Rating Curve= 0 ,0
Exp/Cntr(USF)=0,0
Exp/Cntr=0.3,0.1

Type RM Length L Ch R = 1 ,3297    ,61.6,62.1,61.6
XS GIS Cut Line= 6
2262698.02796557705061.6628862642263006.34255959704929.528060256
2263121.96053235704896.4943537542263152.16486578704883.404774684
2263284.41019129704799.0332050052263511.65477369   704596.275156
#Sta/Elev= 30
       0 1985.84    15.4  1988.2    37.2 1981.52    58.9 1978.64    67.6  1974.3
    76.3 1972.94   119.8 1973.25   132.9 1971.63   145.2 1968.07   172.1 1967.71
   185.1 1965.73   228.6 1962.78   272.2 1961.86   297.5 1960.03   336.7 1959.93
   353.4 1958.32   428.9 1956.91   449.7 1955.76  462.851952.492   471.2 1951.52
  478.891952.494   488.6 1955.93   537.1 1958.27   585.5 1959.79   650.7 1959.86
     780 1964.44   800.8 1964.18   822.4 1965.85   873.4  1966.5   950.2 1970.29
#Mann= 10, -1 ,  0
       0    0.06       0      60    0.07       0     160    0.08       0
     270    0.07       0     330    0.06       0  462.85   0.045       0
  478.89    0.06       0  582.12    0.07       0  745.66    0.06       0
  895.66     0.1       0
Bank Sta=462.85,478.89
XS Rating Curve= 0 ,0
Exp/Cntr(USF)=0,0
Exp/Cntr=0.3,0.1

Type RM Length L Ch R = 1 ,3235    ,108.9,105.4,102.4
XS GIS Cut Line= 6
2262717.33897819 705118.425559722263025.65357221704986.290733712
2263141.27154497704953.257027209 2263171.4758784 704940.16744814
2263303.72120391704855.7958784612263530.96578631704653.037829455
#Sta/Elev= 30
       0 1986.05    11.8 1984.99    42.7 1979.75    72.7 1976.81    81.4 1974.94
    90.1 1975.31   103.6 1971.83   131.1 1969.25   142.3 1965.82   177.2 1965.62
   185.9 1963.25   201.1 1961.09   246.7 1959.56   259.8 1961.06   277.2 1956.97
   316.9 1956.96   348.1 1955.12     388 1954.54   425.7 1951.01  455.511950.468
   463.2 1949.32  470.671950.469   476.3 1952.84     485 1954.26   617.4 1955.09
   676.2 1957.86   699.9 1959.84   775.8 1960.27   805.8 1961.95   950.2 1966.41
#Mann= 9, -1 ,  0
       0    0.06       0      40    0.07       0     220    0.08       0
     250    0.07       0  455.51   0.045       0  470.67    0.07       0
   508.6    0.06       0  685.66    0.07       0  825.66    0.06       0
#XS Ineff= 2 , 0
          426.55  1954.6
Permanent Ineff=
       F       F
Bank Sta=455.51,470.67
XS Rating Curve= 0 ,0
Exp/Cntr(USF)=0,0
Exp/Cntr=0.3,0.1

Type RM Length L Ch R = 1 ,3130    ,296.5,297.1,296.8
XS GIS Cut Line= 4
2262724.21560468705167.6973651232263107.02393925705088.709067077
2263230.29371006705005.1600180522263626.92654118704724.692327012
#Sta/Elev= 30
       0 1987.85    56.3 1979.57    77.6 1977.91   110.2 1972.18   118.4 1969.59
   138.8 1968.36   151.1 1963.56   183.8 1963.36   191.7 1959.71   200.1 1957.49
   224.6 1954.65   253.2 1952.61   285.9 1954.53   298.1 1952.73   330.8 1951.41
   347.4 1952.57   430.9 1950.59   445.4 1946.84   457.6 1945.33  468.921946.885
   488.9 1949.96     547 1950.35   612.9 1952.95   658.8 1953.02   747.7 1955.91
   879.2 1958.31   922.8 1962.56   955.4 1964.23   973.2 1966.73  1025.6 1970.21
#Mann= 11, -1 ,  0
       0    0.05       0      30    0.06       0     190    0.07       0
  430.87    0.06       0   445.4   0.045       0  468.92    0.06       0
  500.87    0.07       0  549.79    0.06       0  669.79    0.07       0
  789.79    0.06       0  919.79     0.1       0
Bank Sta=445.4,468.92
XS Rating Curve= 0 ,0
Exp/Cntr(USF)=0,0
Exp/Cntr=0.3,0.1