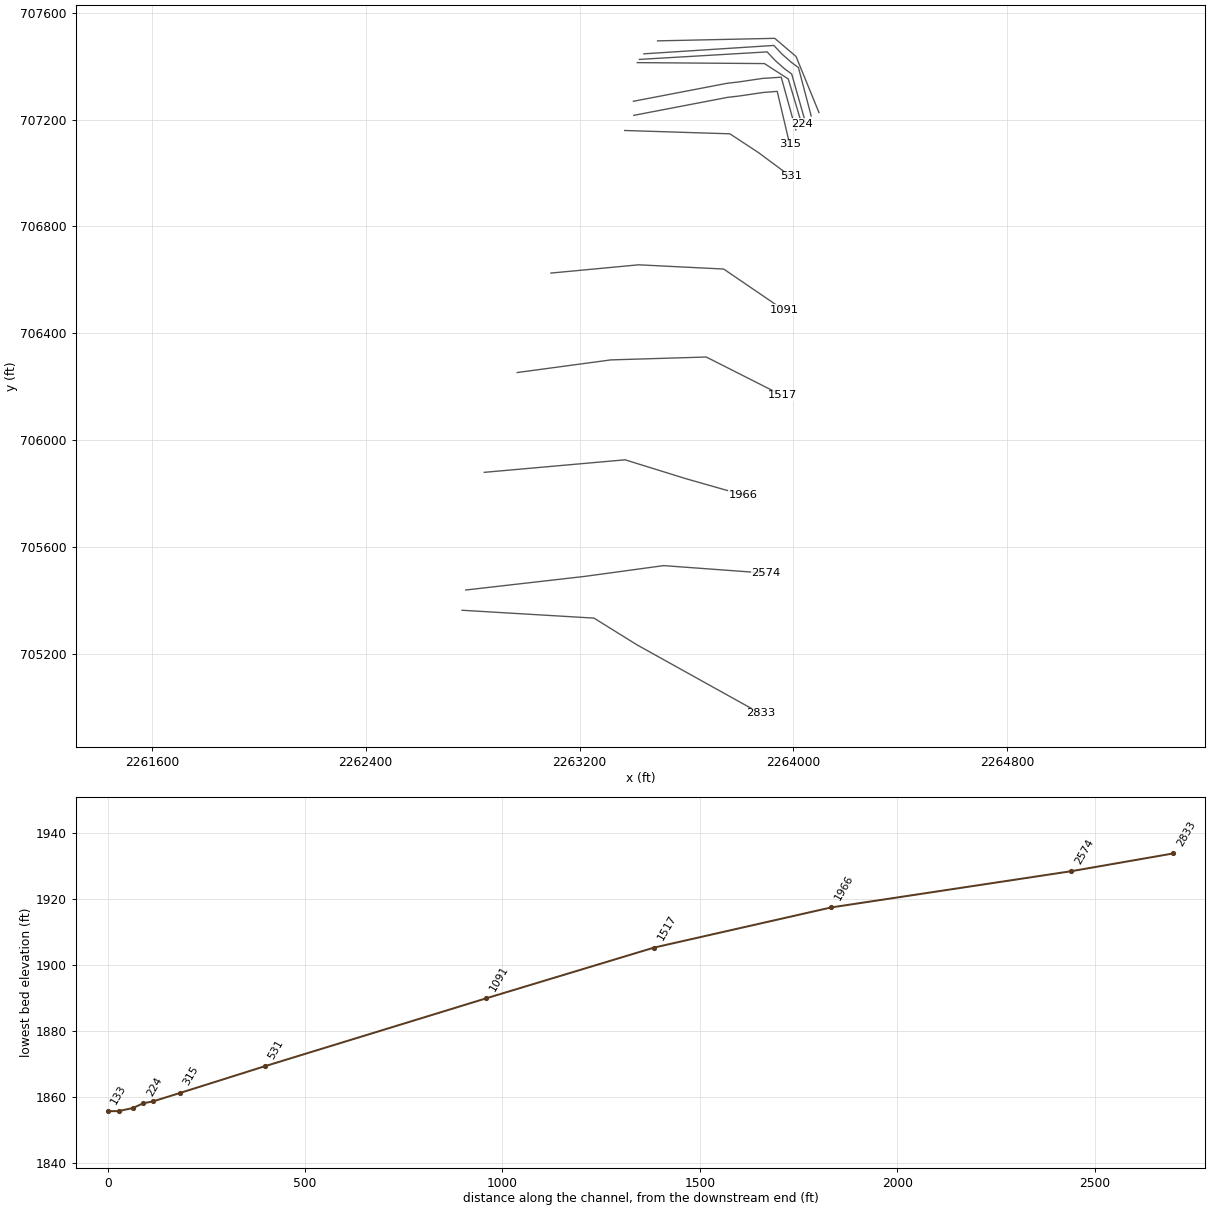
HEC-RAS study GRASSYRN.prj: GRASSYRN

--- GRASSYRN.g01 (geometry) --- (continued)

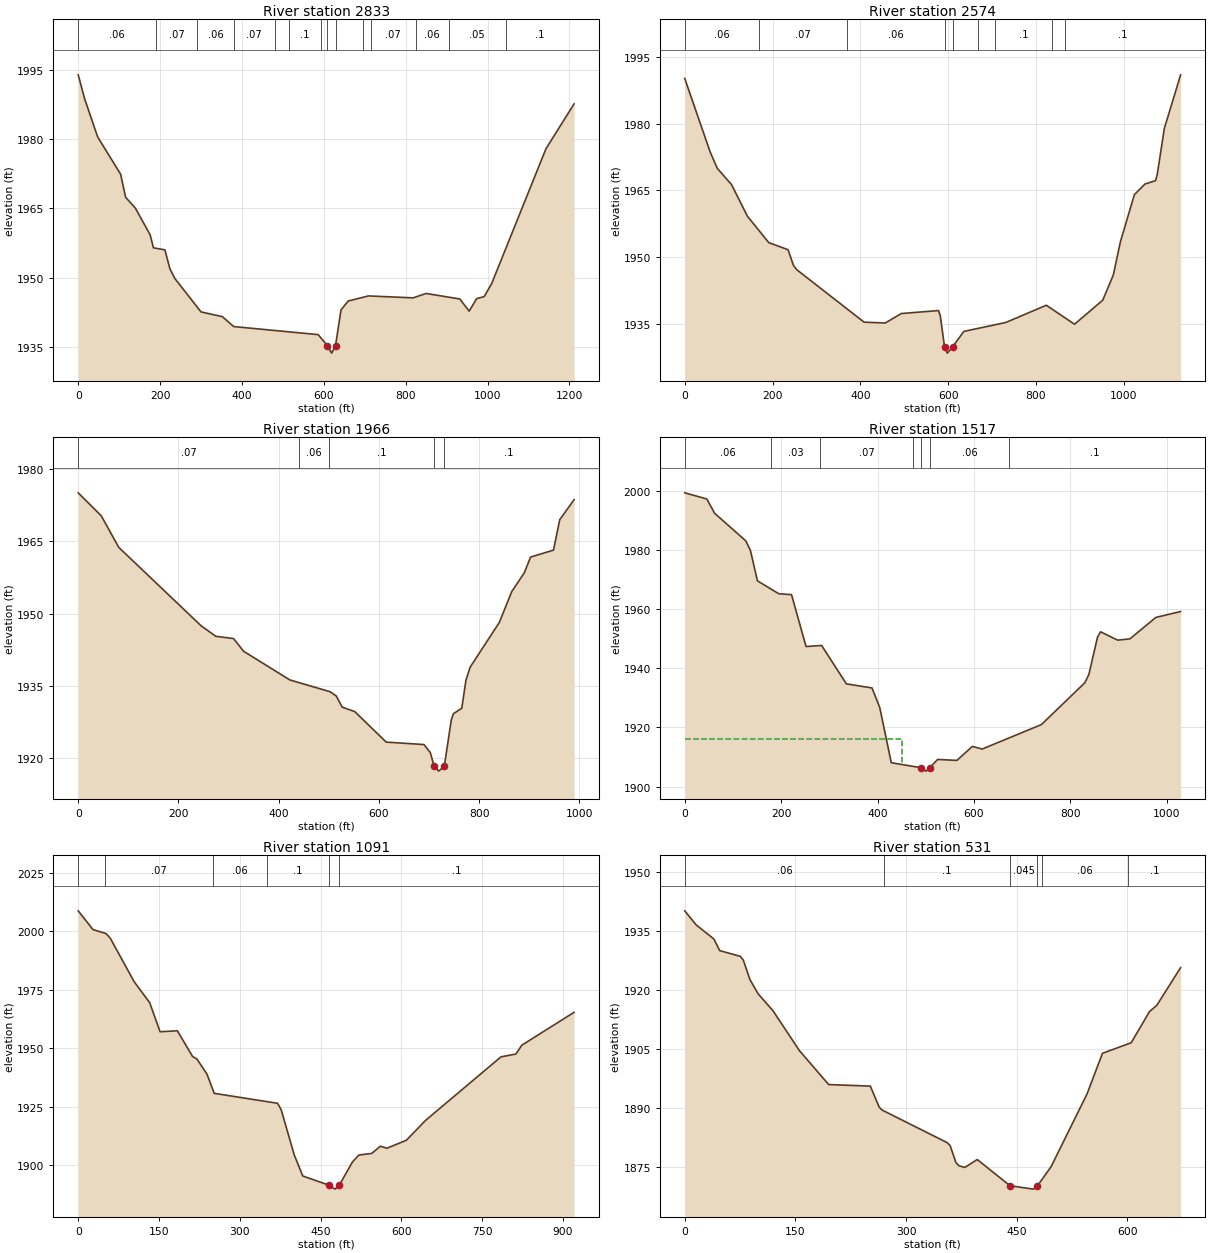
Type RM Length L Ch R = 1 ,2833    ,250.3,258.4,263.8
XS GIS Cut Line= 4
2262760.71651898705363.9008291712263253.98226879 705334.57238767
2263415.77152717705234.0699184382263876.18088395 704978.11893376
#Sta/Elev= 30
       0 1993.87    15.5 1988.75    47.5 1980.44   103.6 1972.39   115.8  1967.4
   139.7 1965.04   175.8 1959.27   183.8 1956.47   211.8 1956.03   223.9 1951.96
   235.9 1949.86     300 1942.61   352.1 1941.59     380 1939.44   586.2  1937.7
  608.911935.318   619.2  1933.7   628.6  1935.3     642 1943.04   659.4 1944.96
   709.1 1946.07   818.2 1945.65   849.8  1946.6   932.2 1945.41   955.1 1942.77
   973.4 1945.48   991.7 1945.92    1010 1948.72  1142.7 1977.89  1211.4 1987.59
#Mann= 14, -1 ,  0
       0    0.06       0     190    0.07       0     290    0.06       0
     380    0.07       0     480    0.08       0  514.14     0.1       0
  594.14    0.05       0  608.91   0.045       0   628.6    0.05       0
   694.6    0.06       0   714.6    0.07       0   824.6    0.06       0
   904.6    0.05       0  1044.6     0.1       0
Bank Sta=608.91,628.6
XS Rating Curve= 0 ,0
Exp/Cntr(USF)=0,0
Exp/Cntr=0.3,0.1

Type RM Length L Ch R = 1 ,2574    ,609.1,608.7,600.4
XS GIS Cut Line= 4
2262774.31724545705439.6980789572263218.84381134705490.540041112
2263514.69080823705530.9289445122263897.15866767705502.857908957
#Sta/Elev= 30
       0 1990.22    58.2 1973.58    74.3 1969.95   106.5 1966.32   142.8 1959.18
   191.4 1953.23   235.4 1951.63   247.5 1948.14     255 1947.14   408.5 1935.31
   456.8 1935.12   493.2 1937.25     578 1937.92     582 1936.79   591.81929.706
   598.1 1928.33  609.911929.707   635.7 1933.22   731.4 1935.24   823.6 1939.12
   887.9 1934.84   952.1 1940.26   976.1  1945.9   992.4 1953.44  1024.2 1964.04
  1048.3 1966.43  1072.4 1967.19  1076.4 1968.65  1092.4 1978.96  1129.5 1991.04
#Mann= 9, -1 ,  0
       0    0.06       0     170    0.07       0     370    0.06       0
   591.8   0.045       0  609.91    0.06       0  667.42    0.05       0
  707.42     0.1       0  836.02    0.05       0  866.02     0.1       0
Bank Sta=591.8,609.91
XS Rating Curve= 0 ,0
Exp/Cntr(USF)=0,0
Exp/Cntr=0.3,0.1

Type RM Length L Ch R = 1 ,1966    ,446.4,449.1,453.4
XS GIS Cut Line= 4
2262843.50159306705879.940721536 2263370.4412235705926.825038866
2263599.38056784 705855.75335634 2263811.7048792705795.355099034
#Sta/Elev= 30
       0 1974.99      46 1970.23      81 1963.69   245.6 1947.43   274.7 1945.28
   309.9 1944.82     330 1942.19   422.3 1936.25   502.7 1933.81   515.1 1932.91
   526.7 1930.62   551.8  1929.7   614.6 1923.38     690 1922.87   702.6 1921.21
  710.191918.394   719.3 1917.37  730.551918.394   744.4 1927.93   748.6 1929.24
   765.4  1930.4   773.7 1936.19     782 1938.87   840.3 1948.16   865.2 1954.56
   890.2 1958.44   902.6 1961.68   948.4 1963.13   960.9 1969.44   989.5 1973.57
#Mann= 5, -1 ,  0
       0    0.07       0     440    0.06       0     500     0.1       0
  710.19   0.045       0  730.55     0.1       0
Bank Sta=710.19,730.55
XS Rating Curve= 0 ,0
Exp/Cntr(USF)=0,0
Exp/Cntr=0.3,0.1

Type RM Length L Ch R = 1 ,1517    ,422.8,425.4,423.3
XS GIS Cut Line= 4
2262966.74015142706253.3461979232263317.33253553706300.635526778
2263674.08586663706311.4042066822263958.07474802706167.759419341
#Sta/Elev= 30
       0 1999.48    45.8  1997.4      62 1992.56   126.6 1983.22   136.3 1979.98
   150.8 1969.68   195.2 1965.29   221.6 1964.99   251.7 1947.42     284 1947.78
   335.4 1934.78   388.6 1933.39   404.6 1926.76   428.6 1908.06  489.261906.409
   500.7 1905.22  508.571906.408   524.7 1909.18   564.7 1908.85   596.7 1913.59
   617.3 1912.71   739.9 1920.97     830 1935.12   838.5 1937.94   856.5 1950.62
   862.7 1952.41   898.5 1949.58   923.7 1950.02   977.5 1957.28  1028.9 1959.28
#Mann= 7, -1 ,  0
       0    0.06       0     180    0.03       0     280    0.07       0
  473.77    0.06       0  489.26   0.045       0  508.57    0.06       0
  673.77     0.1       0
#XS Ineff= 2 , 0
          450.25 1916.18
Permanent Ineff=
       F       F
Bank Sta=489.26,508.57
XS Rating Curve= 0 ,0
Exp/Cntr(USF)=0,0
Exp/Cntr=0.3,0.1

Type RM Length L Ch R = 1 ,1091    ,563,560.1,554.1
XS GIS Cut Line= 4
2263092.83648599706625.4749233952263421.17676167706656.391256666
2263739.26831678706640.5603522082263964.30244655706487.206062421
#Sta/Elev= 30
       0 2008.71    27.5 2000.69    51.6 1999.01    59.6    1997   103.8 1978.47
   132.7  1969.5     152 1957.07   184.1 1957.49   212.3 1946.52   220.3 1945.46
   239.1 1938.96   252.5 1930.78   370.1 1926.53   376.8 1923.79   401.2 1904.42
   416.9  1895.5   464.81891.623     477 1889.88     485 1891.68     509 1901.43
     521 1904.44   545.1 1905.13   560.8  1908.2   573.1 1907.35   609.1 1910.73
   645.2  1919.3   784.9 1946.37   812.6 1947.56   823.6 1951.35   920.6 1965.38
#Mann= 6, -1 ,  0
       0    0.06       0      50    0.07       0     250    0.06       0
  349.79     0.1       0   464.8   0.045       0     485     0.1       0
Bank Sta=464.8,485
XS Rating Curve= 0 ,0
Exp/Cntr(USF)=0,0
Exp/Cntr=0.3,0.1

Type RM Length L Ch R = 1 ,531     ,203.4,216,222.1
XS GIS Cut Line= 4
 2263368.7830121707158.9757742582263762.53622799707146.515748817
2263868.76359678707076.7082479692263990.05659387706986.869163052
#Sta/Elev= 30
       0 1940.21    15.4 1936.64    39.4 1933.06    47.4 1930.09    75.4 1928.62
    79.4 1927.66    88.4  1922.7    99.4  1919.1   119.5 1914.81   155.5 1904.61
   195.1 1895.99   251.5  1895.6   263.5 1890.26   267.5  1889.5   355.6 1881.22
   359.6 1880.48   367.6 1876.12   371.6 1875.33   379.6 1874.91   396.4 1876.91
  440.871870.238   472.5 1869.38  478.021870.237   496.4 1875.07   545.2 1893.61
   566.1 1903.95     605 1906.63   629.8 1914.56   639.8 1916.18     672 1925.76
#Mann= 6, -1 ,  0
       0    0.06       0     270     0.1       0  440.87   0.045       0
  478.02     0.1       0  483.95    0.06       0  601.06     0.1       0
Bank Sta=440.87,478.02
XS Rating Curve= 0 ,0
Exp/Cntr(USF)=0,0
Exp/Cntr=0.3,0.1

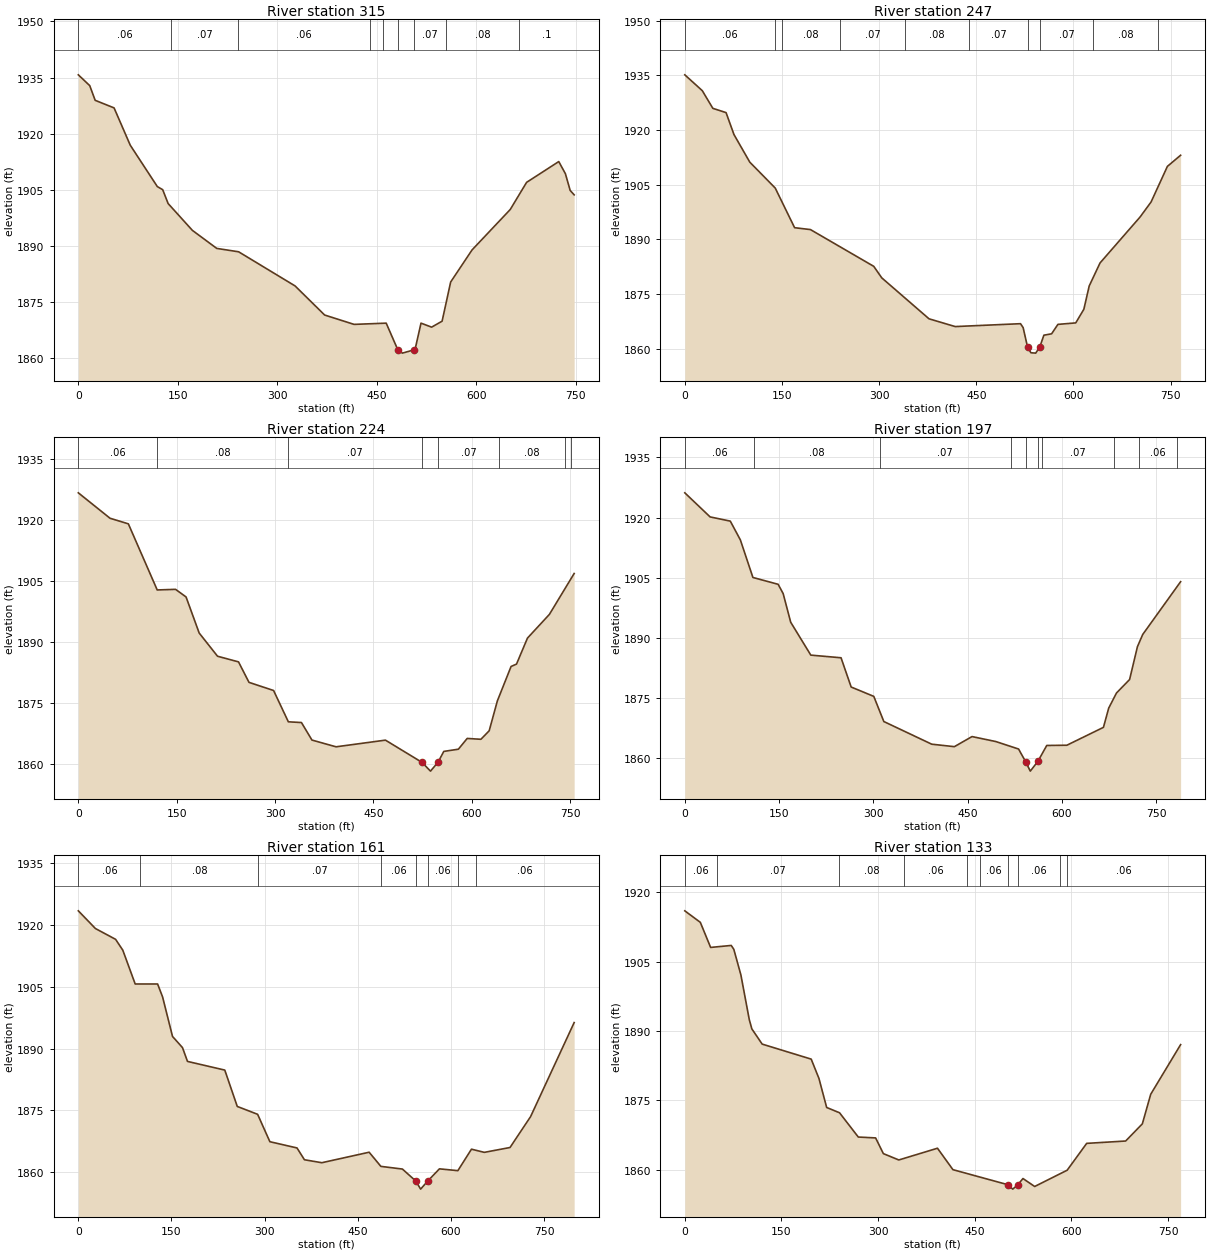
Type RM Length L Ch R = 1 ,315     ,73.1,67.8,69.3
XS GIS Cut Line= 6
2263403.24098749707215.6553018312263754.56865794707283.042662272
2263796.67185504707287.8709983922263886.25739812707301.095530942
2263939.58212615707305.3615091852263986.26599224707107.330082565
#Sta/Elev= 30
       0 1935.72    17.2 1932.83    25.4  1928.9    53.9 1926.87    78.3 1916.89
   119.1 1905.82   127.2 1904.99   135.4 1901.28     172  1894.1   208.7 1889.28
   241.7 1888.37   326.8 1879.24   371.4 1871.45   415.8 1868.95   464.2 1869.28
  481.84  1862.1   488.6 1861.26   505.4  1862.1   508.6 1862.94   516.7 1869.28
   532.7 1868.21   548.5 1869.81   561.4 1880.29   593.7 1888.88   651.2 1899.68
   675.9 1906.95   724.4 1912.51   734.4 1909.26   741.6 1904.79   747.6 1903.61
#Mann= 9, -1 ,  0
       0    0.06       0     140    0.07       0     240    0.06       0
  439.39    0.08       0  459.39    0.07       0  481.84   0.045       0
   505.4    0.07       0  554.16    0.08       0  664.16     0.1       0
Bank Sta=481.84,505.4
XS Rating Curve= 0 ,0
Exp/Cntr(USF)=0,0
Exp/Cntr=0.3,0.1

Type RM Length L Ch R = 1 ,247     ,28.1,23.7,16.2
XS GIS Cut Line= 6
2263401.66099555707268.321699882  2263752.988666707335.709060324
 2263795.0918631707340.5373964432263884.67740618707353.761928994
2263954.63839657707358.3586995592264009.26365272707161.166845018
#Sta/Elev= 30
       0 1935.13      27 1930.78    43.3 1925.93    63.7 1924.76    75.9 1918.74
   100.3 1911.17   139.6 1904.05   169.5 1893.17     194 1892.65   291.7 1882.56
     304 1879.41     377 1868.16   417.4 1866.03   518.3 1866.82   522.3 1865.74
  529.09 1860.42   534.3 1858.84   541.7 1858.74  547.971860.421   554.3 1863.66
   566.2 1864.04     576 1866.63   603.5 1867.04     616 1870.77   624.3 1877.18
     641 1883.49   702.8  1896.1   719.8 1900.23     745    1910   765.4 1913.06
#Mann= 10, -1 ,  0
       0    0.06       0     140    0.07       0     150    0.08       0
     240    0.07       0     340    0.08       0  439.39    0.07       0
  529.09   0.045       0  547.97    0.07       0   630.8    0.08       0
   730.8     0.1       0
Bank Sta=529.09,547.97
XS Rating Curve= 0 ,0
Exp/Cntr(USF)=0,0
Exp/Cntr=0.3,0.1

Type RM Length L Ch R = 1 ,224     ,28.5,26.9,26.5
XS GIS Cut Line= 4
2263415.83703162707412.8861344212263891.78574014707409.296475812
2263980.91624555707351.8953685752264030.79759655707184.970949569
#Sta/Elev= 30
       0 1926.66    48.3 1920.41    76.3 1919.03   120.3 1902.77   148.3 1902.92
   164.3 1901.05   184.3 1892.18   212.3 1886.47   244.3 1885.08   260.3 1880.04
   297.8 1878.04   320.3 1870.34   340.3 1870.16   356.3 1865.85   393.1 1864.19
   468.4 1865.83  524.071860.374   537.1 1858.21  548.471860.375   557.4 1863.06
   579.6  1863.6   593.1 1866.25     614 1866.04   626.6 1868.13   639.1 1875.49
     660 1883.95   668.3 1884.54     685 1890.93   718.4 1896.75   756.2 1906.82
#Mann= 8, -1 ,  0
       0    0.06       0     120    0.08       0     320    0.07       0
  524.07   0.045       0  548.47    0.07       0  641.98    0.08       0
  741.98    0.06       0  751.98     0.1       0
Bank Sta=524.07,548.47
XS Rating Curve= 0 ,0
Exp/Cntr(USF)=0,0
Exp/Cntr=0.3,0.1

Type RM Length L Ch R = 1 ,197     ,35.1,35.5,35.1
XS GIS Cut Line= 6
2263423.97731138707424.879771999 2263901.7924976707452.984827356
2263932.56222656 707420.369264422263967.08209589707389.892262662
2263993.72191133 707370.279216982264044.78969831707191.112765141
#Sta/Elev= 30
       0 1926.17    40.3 1920.16    72.4 1919.11    88.4 1914.43   108.4 1905.05
   148.5 1903.35   156.5 1901.03   168.5 1893.89   200.5 1885.68   248.6 1885.02
   264.7 1877.72   300.7 1875.39   316.7 1869.11   392.9 1863.46   428.9 1862.84
     457 1865.36   494.9 1864.12   531.1 1862.25   542.5 1859.03   549.7 1856.74
   561.71859.148   575.9 1863.14   607.9  1863.2   666.1 1867.66   674.5 1872.47
   686.9 1876.24   707.7 1879.59   720.2 1887.79   728.6 1890.83   788.9    1904
#Mann= 10, -1 ,  0
       0    0.06       0     110    0.08       0     310    0.07       0
  518.64    0.06       0   542.5   0.045       0   561.7    0.06       0
  568.82    0.07       0  682.61    0.08       0  722.61    0.06       0
  782.61     0.1       0
Bank Sta=542.5,561.7
XS Rating Curve= 0 ,0
Exp/Cntr(USF)=0,0
Exp/Cntr=0.3,0.1

Type RM Length L Ch R = 1 ,161     ,28.7,28.3,30.1
XS GIS Cut Line= 6
2263440.74098511707445.7949950632263927.00880312707477.151062645
2263957.77853207707444.5354997092263992.29840141707414.058497951
2264018.93821685707394.445452269 2264066.7549916707213.328393095
#Sta/Elev= 30
       0 1923.49    27.5 1919.19      60 1916.56    71.6 1913.93    91.6  1905.7
   127.7  1905.7   135.7 1902.56   151.7 1892.95   167.8 1890.23   175.8 1886.88
   235.9 1884.77     256 1875.93   288.8 1874.02   308.5 1867.36   352.2 1865.84
   364.2 1862.97   392.2 1862.25   468.4  1864.8   487.3 1861.36     522 1860.71
  543.571857.789   551.3 1855.83  562.681857.784   581.6 1860.76   611.3 1860.32
   633.2 1865.54   653.9 1864.77   695.3 1865.95   728.4 1873.45   798.6 1896.32
#Mann= 8, -1 ,  0
       0    0.06       0     100    0.08       0     290    0.07       0
  487.28    0.06       0  543.57   0.045       0  562.68    0.06       0
  611.25    0.07       0  641.25    0.06       0
Bank Sta=543.57,562.68
XS Rating Curve= 0 ,0
Exp/Cntr(USF)=0,0
Exp/Cntr=0.3,0.1

Type RM Length L Ch R = 1 ,133     ,,,
XS GIS Cut Line= 4
2263492.05876124707494.2692715542263930.41829045707503.746732252
2264010.00306973707435.8655969862264095.78824929707226.148511507
#Sta/Elev= 30
       0    1916    24.1 1913.51    40.1 1908.08    72.1 1908.51    76.1 1907.67
    87.1 1902.11   100.1 1892.45   104.1 1890.45   120.1 1887.16   196.2 1883.91
   208.2 1879.74   220.2 1873.45   240.2  1872.3   269.3 1867.05   296.2 1866.86
   308.2 1863.46   332.2 1862.09   392.2 1864.63   416.2 1859.99   501.1 1856.75
   509.1 1855.78  516.98 1856.74   524.9 1858.07   543.1 1856.35   593.5 1859.87
   623.8 1865.68   684.3 1866.19   710.2 1869.91   723.2 1876.31   769.6 1887.05
#Mann= 10, -1 ,  0
       0    0.06       0      50    0.07       0     240    0.08       0
     340    0.06       0  438.46    0.07       0  458.46    0.06       0
   501.1   0.045       0  516.98    0.06       0  583.06    0.08       0
  593.06    0.06       0
Bank Sta=501.1,516.98
XS Rating Curve= 0 ,0
Exp/Cntr(USF)=0,0
Exp/Cntr=0.3,0.1
LCMann Table=0

Chan Stop Cuts=-1
Use User Specified Reach Order=0
Composite Channel Slope=5